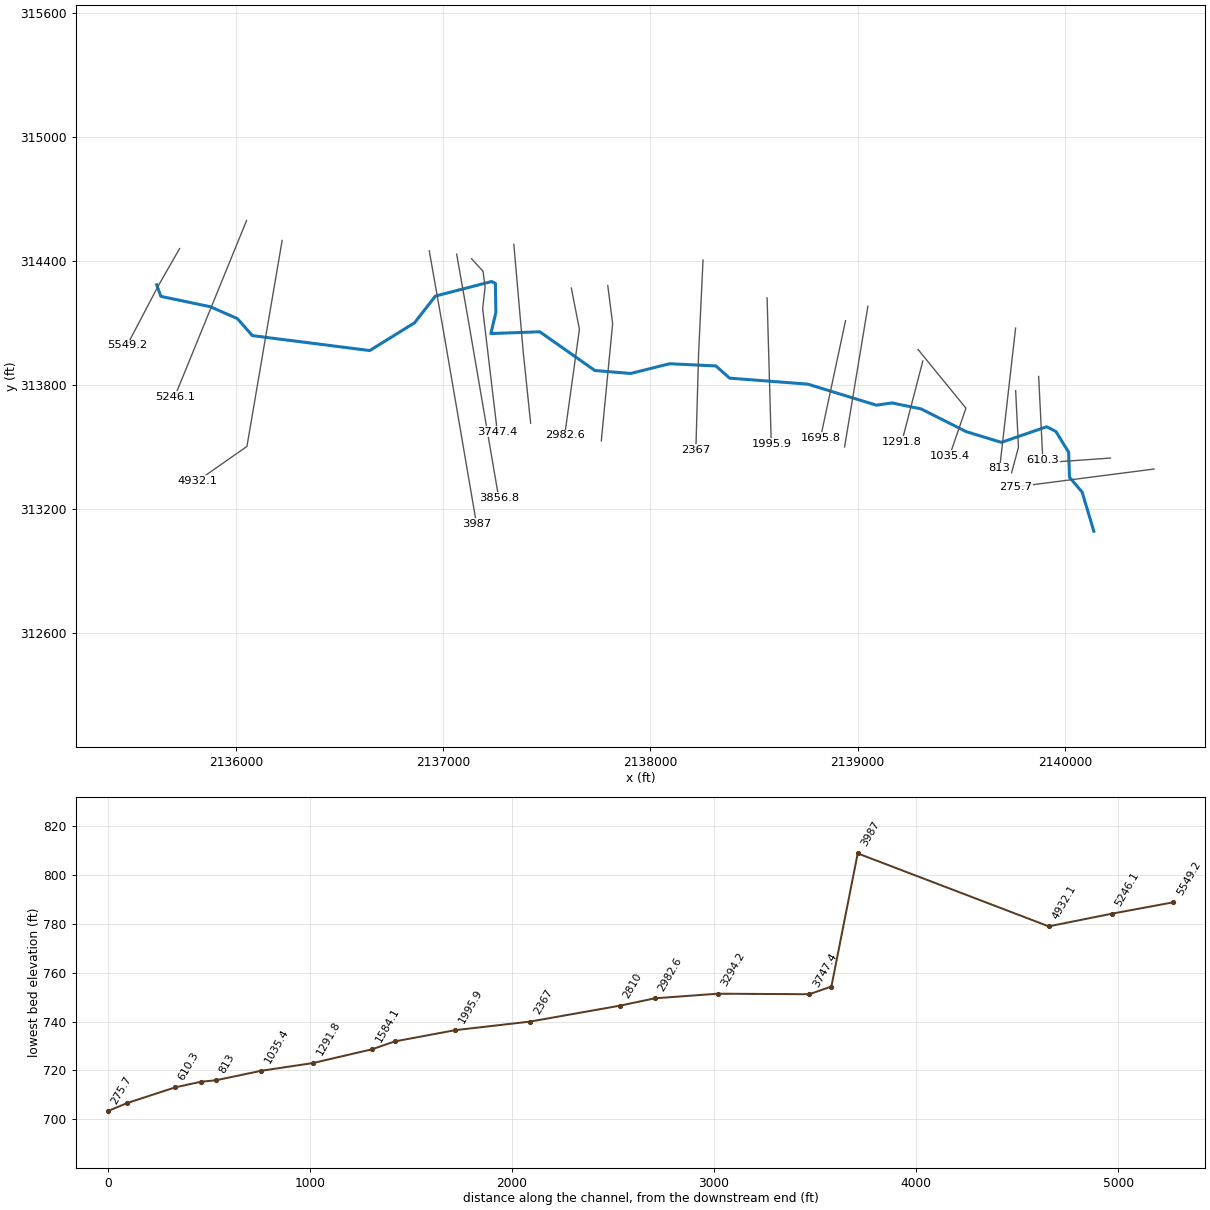
--- NP62.prj (project) ---

Proj Title=NP62
Current Plan=p01
Default Exp/Contr=0,0
English Units
Geom File=g01
Flow File=f01
Plan File=p01
BEGIN DESCRIPTION:
END DESCRIPTION:
DSS Export Rating Curves= 0
DSS Export Rating Curve Sorted= 0
DSS Export Volume Flow Curves= 0
DXF OffsetX= 0
DXF OffsetY= 0
DXF ScaleX= 0
DXF ScaleY= 0

--- NP62.p01 (plan) ---

Plan Title=Floodplain
Program Version=4.00
Geom File=g01
Flow File=f01
K Sum by GR=0
Std Step Tol=0.01
Critical Tol=0.01
Num of Std Step Trials=20
Max Error Tol=0.3
Flow Tol Ratio=0.001
Split Flow NTrial=30
Split Flow Tol=0.02
Split Flow Ratio=0.02
Log Output Level=0
Friction Slope Method=1
Unsteady Friction Slope Method=2
Unsteady Bridges Friction Slope Method=1
Global Log Level=0
CheckData=False
Run HTab=0
Run UNet=0
Run PostProcess=0
UNET Theta=0
UNET Theta Warmup=0
UNET ZTol=0
UNET ZSATol=0
UNET MxIter=0
UNET MaxInSteps=0
UNET DtIC=0
UNET DtMin=0
UNET MaxCRTS=0
UNET WFStab=0
UNET SFStab=0
UNET WFX=0
UNET SFX=0
UNET DSS MLevel=0
UNET DZMax Abort=0
UNET Convert EG Bridges=0
UNET Use Existing IB Tables=0
UNET Froude Limit=0
UNET Froude Power=0
Write IC File=0
Echo Input=False
Echo Output=False
Write Detailed=0

--- NP62.f01 (steady flow) ---

Flow Title=NFF Regression Equation
Program Version=4.00
Number of Profiles=1
Profile Names=P100yr
River Rch & RM=NP62,Main      ,5549.2
     217
River Rch & RM=NP62,Main      ,3987
     229
River Rch & RM=NP62,Main      ,2367
     253
River Rch & RM=NP62,Main      ,275.7
     273
Boundary for River Rch & Prof#=NP62,Main      ,1
Up Type=0
Dn Type=3
Dn Slope=0.026599

--- NP62.g01 (geometry) ---

Geom Title=USGS 10m DEM
Program Version=4.00

River Reach=NP62            ,Main
Reach XY= 30
     2135616.642      314284.343     2135636.777      314228.239
     2135875.099      314178.213     2136006.206      314120.704
     2136078.655      314038.263     2136645.041      313966.082
     2136861.285      314100.178      2136962.03      314229.707
      2137233.45      314300.023     2137251.644      314290.927
     2137253.918      314149.926     2137229.722      314048.367
     2137465.971      314056.857     2137731.662      313869.645
     2137904.579      313855.227      2138092.87      313902.279
     2138315.673      313891.738     2138382.002       313832.71
     2138759.644       313803.67     2139090.898      313701.785
      2139165.29      313712.788     2139306.217      313683.877
     2139524.907      313573.548     2139694.238      313522.054
     2139912.579      313597.471      2139956.91       313574.75
     2140018.592      313474.418     2140022.775      313353.364
     2140083.648      313281.664     2140140.246      313092.149

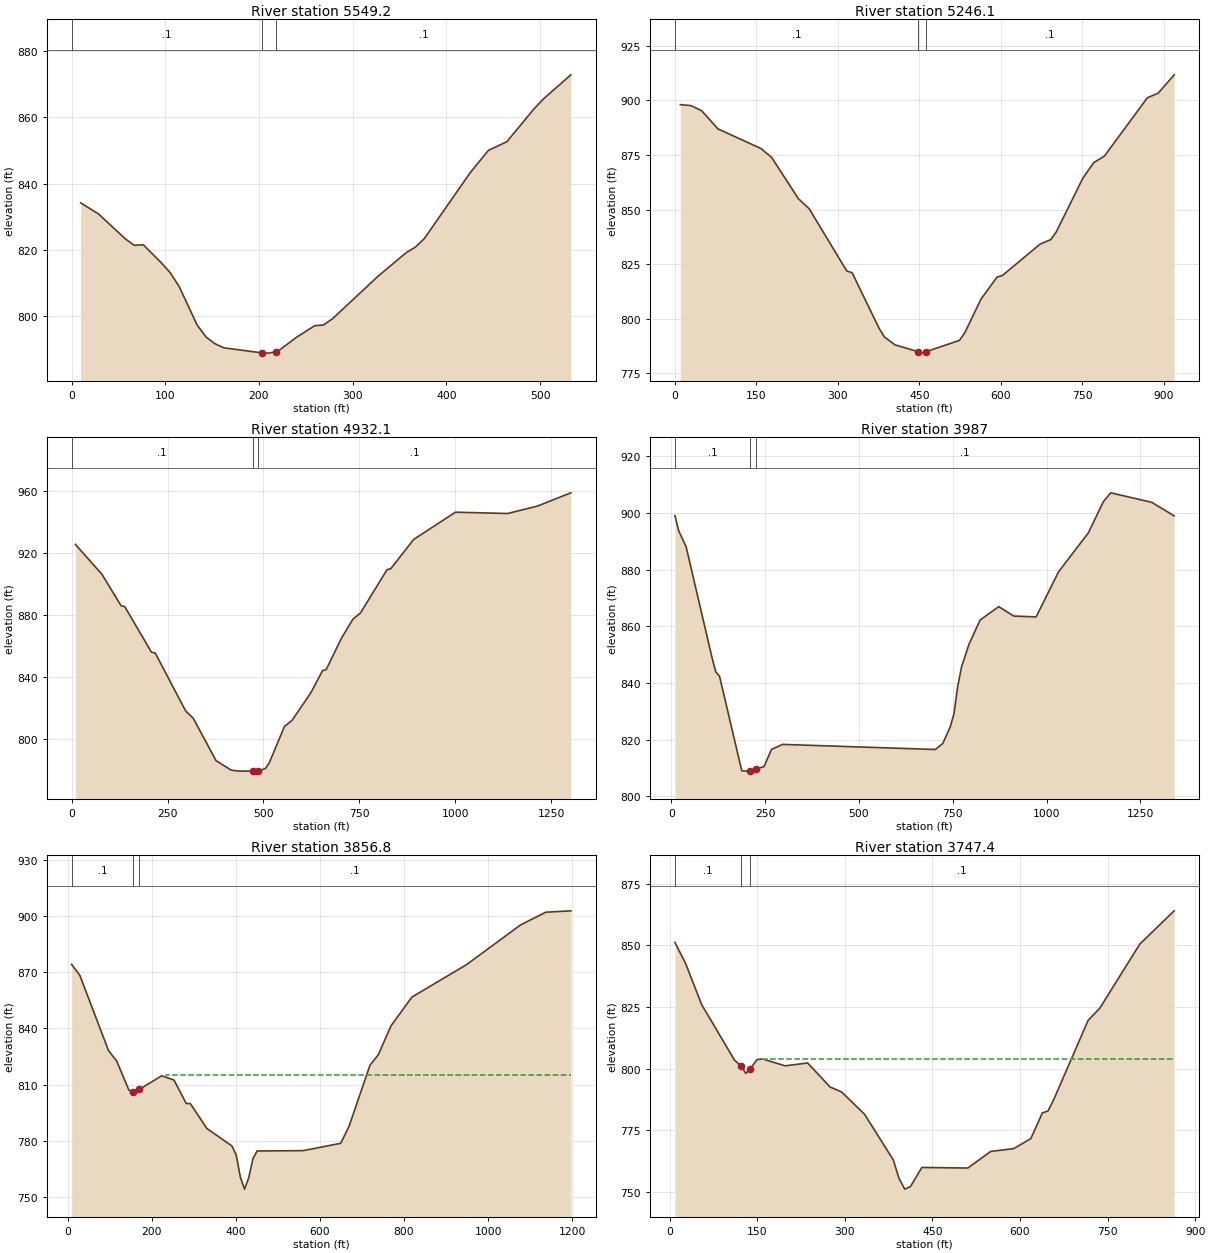
Type RM Length L Ch R = 1 ,5549.2  ,295.5,303.1,307.2
XS GIS Cut Line= 3
     2135727.246      314459.351     2135622.976      314276.604
     2135473.561       313990.81
#Sta/Elev= 30
     9.6   834.2    28.7  830.86    57.4  823.32    66.9  821.39    76.5  821.56
    95.6  816.15   105.2  813.13   114.8  808.95   133.9  797.37   143.5  793.72
     153  791.69   162.6  790.45   202.9  788.94   210.4  788.85   217.9  789.28
   220.2  789.41   239.7  793.56   259.3   797.1     269  797.36   278.8  799.31
   327.7  812.21     357  819.13   366.8  820.82   376.5  823.42   425.4  843.28
   444.9  850.05   464.5  852.64   493.8  862.63   503.6  865.56   532.9  872.84
#Mann= 3 , 0 , 0
       0      .1       0   202.9    .045       0   217.9      .1       0
Bank Sta=202.9,217.9
XS Rating Curve= 0 ,0
Exp/Cntr=0.3,0.1

Type RM Length L Ch R = 1 ,5246.1  ,309.1,314,319
XS GIS Cut Line= 2
      2136050.71      314595.264     2135704.062      313743.586
#Sta/Elev= 30
     9.9  898.09    29.7  897.64    49.4  895.25    79.1  886.98   158.2  878.01
     178  873.92   227.4  854.97   247.2  850.39   316.4  821.86   326.3  821.05
   375.7  795.71   385.6  791.64   405.4  787.98   447.2  784.94   454.8  784.21
   462.2  784.84     524  790.07   533.9  793.56   563.6  808.94   593.2  819.08
   603.1  819.77   672.3  834.14   692.1  836.23     702  839.62   751.4  864.45
   771.2  871.49     791  874.51   870.1  901.25   889.9  903.31   919.5  911.75
#Mann= 3 , 0 , 0
       0      .1       0   447.2    .045       0   462.2      .1       0
Bank Sta=447.2,462.2
XS Rating Curve= 0 ,0
Exp/Cntr=0.3,0.1

Type RM Length L Ch R = 1 ,4932.1  ,937.3,945.1,952.8
XS GIS Cut Line= 3
     2136222.368      314498.882     2136052.387      313502.442
     2135814.169      313335.312
#Sta/Elev= 30
     9.9  925.41    79.3  906.02   128.8  885.88   138.7  885.19   208.1  855.84
     218  855.26   297.3  817.89   317.1  813.15   376.6  785.75   416.2  779.63
     436  778.99   471.9  779.03   486.9  779.06   505.4  780.73   515.3  784.33
     555  807.84   574.8  811.76   624.3   829.8   654.1  843.82     664  844.66
   703.6  864.83   733.4  877.06   753.2  881.16   822.5  909.09   832.5  909.81
   891.9  928.61  1000.9  946.22  1136.9  945.38  1214.5  950.14  1301.8  958.73
#Mann= 3 , 0 , 0
       0      .1       0   471.9    .045       0   486.9      .1       0
Bank Sta=471.9,486.9
XS Rating Curve= 0 ,0
Exp/Cntr=0.3,0.1

Type RM Length L Ch R = 1 ,3987    ,130.1,130.2,130.3
XS GIS Cut Line= 3
     2136932.436      314448.589     2137011.326      314000.481
     2137160.486      313127.925
#Sta/Elev= 30
     9.9  899.07    19.8  893.76    39.6  888.12   108.8  848.87   118.7  843.91
   128.6   842.4   187.9  809.02   197.8  808.87   210.8  809.09   225.8  809.55
   247.3   810.5   267.1  816.54   296.7  818.31   703.7  816.51   723.5  818.63
   743.4  824.48   753.4  829.16   763.3  838.75   773.3  845.54   793.2   853.6
     823  862.23   872.7  866.96   912.5  863.64   972.2  863.32  1031.9  879.23
  1111.5  893.01  1151.2  903.97  1171.1  907.15  1280.5  903.79  1340.2     899
#Mann= 3 , 0 , 0
     9.9      .1       0   210.8    .045       0   225.8      .1       0
Bank Sta=210.8,225.8
XS Rating Curve= 0 ,0
Exp/Cntr=0.3,0.1

Type RM Length L Ch R = 1 ,3856.8  ,110.5,109.4,108.3
XS GIS Cut Line= 3
     2137064.737      314432.254     2137118.718      314125.632
     2137267.878      313253.076
#Sta/Elev= 30
     9.7  874.13    29.2  868.31    97.3  828.23   116.8  822.62   145.9  807.11
   155.6  806.02   170.6  807.48   223.8  814.76     253  812.51   282.1  800.03
   291.9  799.92   331.2  786.67   390.9  777.34   400.9  772.57   410.8  760.82
   420.7  754.34   430.7  760.31   440.6  770.43   450.6  774.68     560  774.85
   649.5  778.77   669.4  787.93   719.1  820.43     739  826.02   768.9  841.33
   818.6  856.68   947.9   873.9  1077.2  895.18  1136.9  901.94  1196.6  902.68
#Mann= 3 , 0 , 0
     9.7      .1       0   155.6    .045       0   170.6      .1       0
#XS Ineff= 2 , 0
                          233.84          815.28
Permanent Ineff=
       F       F
Bank Sta=155.6,170.6
XS Rating Curve= 0 ,0
Exp/Cntr=0.3,0.1

Type RM Length L Ch R = 1 ,3747.4  ,448.4,453.3,452.5
XS GIS Cut Line= 5
     2137136.717      314410.151     2137192.147      314349.406
     2137201.708      314272.911     2137190.234      314167.729
     2137260.992      313572.979
#Sta/Elev= 30
     9.1  851.23    27.4  842.66    54.8  826.04   111.1  803.49     123  801.03
   130.4  798.11     138  799.97   149.7  803.71   159.3  803.98   197.8  801.19
   236.3  802.35   274.9  792.59   294.6  790.59   333.9  781.52     383  763.04
   392.8  755.52   402.6  751.19   412.4  752.22     432  759.98   510.6  759.74
   549.9  766.48   589.1   767.6   618.6  771.69   638.2  782.06   648.1  782.92
   657.9  787.56   716.8  819.68   736.4  824.46   805.2  850.57   864.1  864.05
#Mann= 3 , 0 , 0
     9.1      .1       0     123    .045       0     138      .1       0
#XS Ineff= 2 , 0
                          157.66          804.09
Permanent Ineff=
       F       F
Bank Sta=123,138
XS Rating Curve= 0 ,0
Exp/Cntr=0.3,0.1

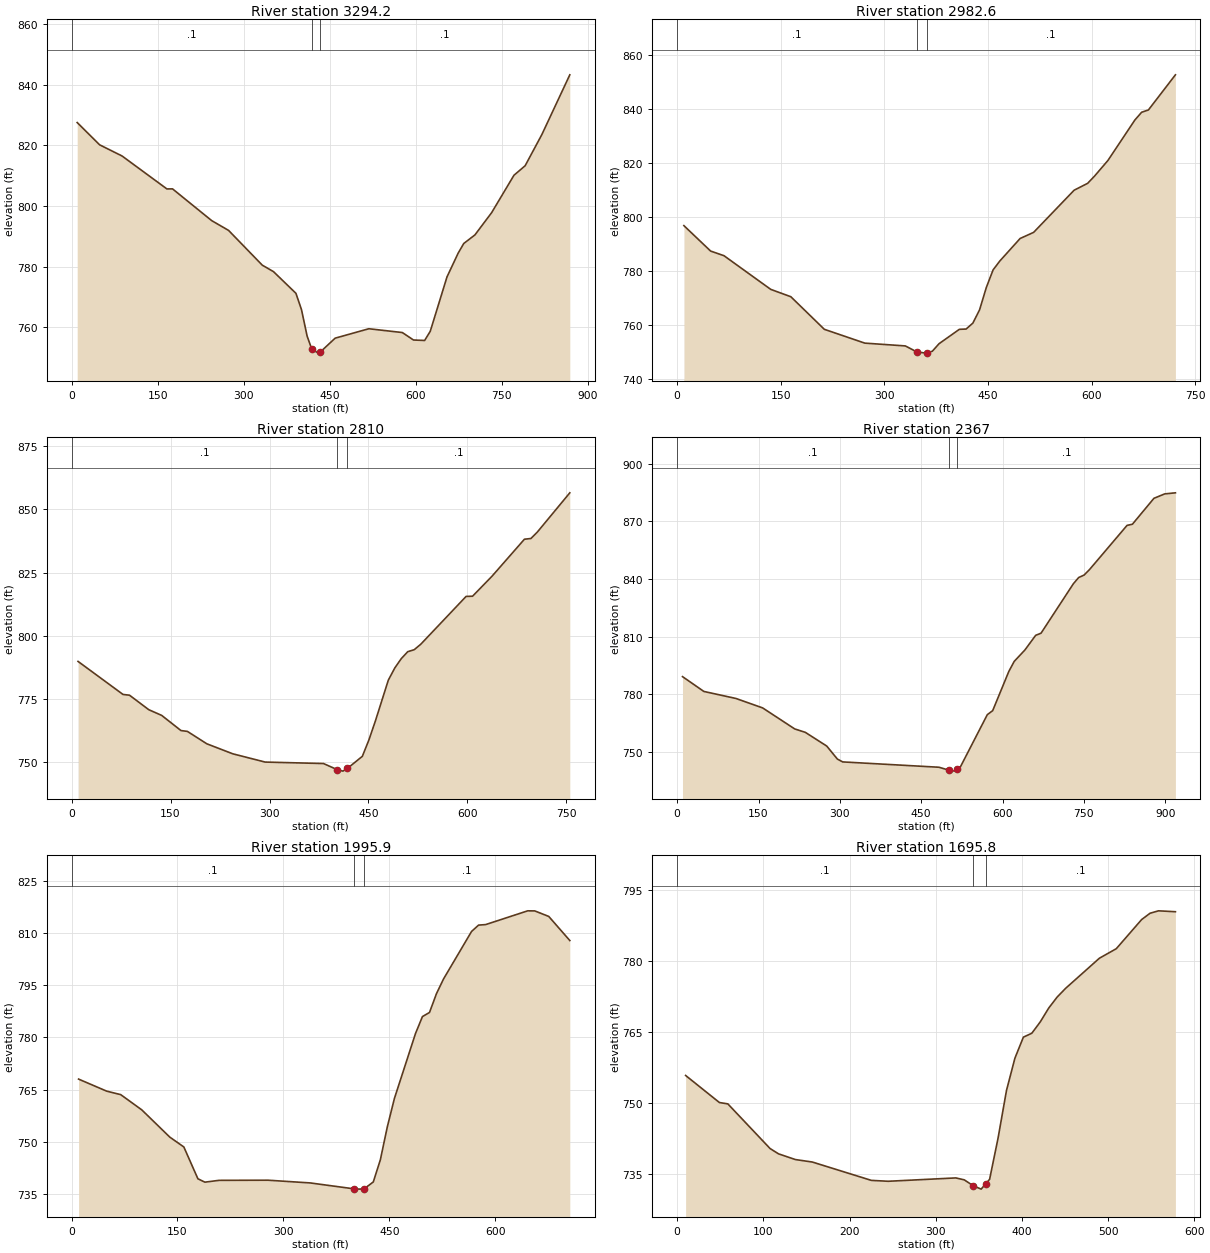
Type RM Length L Ch R = 1 ,3294.2  ,315.9,311.6,307.2
XS GIS Cut Line= 3
     2137340.695      314479.458     2137386.547      313953.525
     2137421.788      313614.689
#Sta/Elev= 30
     9.8  827.55    48.9   820.2      88  816.51   166.2  805.63     176  805.65
   244.4  795.15   273.7  791.94   332.4  780.47     352  778.32   391.1  771.17
   400.8   765.8   410.6  757.06   418.6  752.81   430.2  751.41   433.6  751.77
   459.5  756.35   518.2  759.46   576.6  758.21   596.1  755.74   615.5  755.59
   625.3  758.61   654.5  776.58   673.9   784.4   683.7  787.61   703.1  790.43
   732.3  797.79   771.3  810.16   790.7  813.28   819.9  823.59   868.6  843.31
#Mann= 3 , 0 , 0
       0      .1       0   418.6    .045       0   433.6      .1       0
Bank Sta=418.6,433.6
XS Rating Curve= 0 ,0
Exp/Cntr=0.3,0.1

Type RM Length L Ch R = 1 ,2982.6  ,172.2,172.6,173.2
XS GIS Cut Line= 3
     2137618.142       314268.57     2137657.255      314069.093
     2137586.049      313555.767
#Sta/Elev= 30
     9.7  796.79    48.4  787.36    67.8  785.63   135.5  773.15   164.6  770.42
   213.1  758.34   271.7  753.22   330.4  752.18   346.6  750.02   359.7  749.51
   361.6  749.65   369.5  750.21   379.3  753.02   408.6  758.33   418.4  758.44
   428.2  760.64   437.9  765.56   447.7  773.86   457.5  780.38   467.3  783.69
   496.6  792.01   516.2  794.29   574.8  809.91   594.4  812.47   604.2  815.09
   623.7  820.92   662.8  835.94   672.6  838.82   682.4  839.67   721.5   852.7
#Mann= 3 , 0 , 0
       0      .1       0   346.6    .045       0   361.6      .1       0
Bank Sta=346.6,361.6
XS Rating Curve= 0 ,0
Exp/Cntr=0.3,0.1

Type RM Length L Ch R = 1 ,2810    ,441.3,442.9,444.6
XS GIS Cut Line= 3
     2137794.151      314280.303     2137817.618      314096.472
      2137762.86      313529.334
#Sta/Elev= 30
     9.8  789.88      78  776.81    87.8  776.52     117  770.79   136.6  768.53
   165.8  762.54   175.6   762.2     205   757.3   244.3  753.35   293.4  750.08
   381.8   749.5   402.9  747.05   411.3   746.5   417.9  747.54   440.7  752.36
   450.6  758.82   460.4  766.29     480  782.43   489.9  787.31   499.7  790.98
   509.5  793.72   519.3  794.51   529.2  796.66   597.9  815.57   607.7  815.65
   637.2  823.56   686.3  838.18   696.2  838.48     706  841.05   755.1  856.53
#Mann= 3 , 0 , 0
       0      .1       0   402.9    .045       0   417.9      .1       0
Bank Sta=402.9,417.9
XS Rating Curve= 0 ,0
Exp/Cntr=0.3,0.1

Type RM Length L Ch R = 1 ,2367    ,368.5,371.2,373.5
XS GIS Cut Line= 3
     2138253.912      314404.105     2138232.502      313951.527
     2138219.295      313485.856
#Sta/Elev= 30
     9.8   789.2    49.2  781.48   108.3  777.83   157.6  772.91   216.7  761.98
   236.4  760.18   275.8  753.06   295.5  746.27   305.3   744.8   482.8  742.02
   501.4  740.49   512.6     740   516.4  740.88   522.5   742.3     572   769.4
   581.9  771.48   611.7  791.91   621.6  797.12   641.4  803.09   661.2   810.7
   671.1  811.81   730.6  837.49   740.5  840.79   750.4  842.05   760.4  844.89
   829.7  867.92   839.6  868.53   879.3  882.01   899.1  884.31   918.9  884.87
#Mann= 3 , 0 , 0
       0      .1       0   501.4    .045       0   516.4      .1       0
Bank Sta=501.4,516.4
XS Rating Curve= 0 ,0
Exp/Cntr=0.3,0.1

Type RM Length L Ch R = 1 ,1995.9  ,305.5,300.1,294.7
XS GIS Cut Line= 2
     2138563.123      314220.724     2138583.315      313515.389
#Sta/Elev= 30
     9.9  768.06    49.7   764.6    69.6   763.6    99.4  759.23   139.1  751.41
     159  748.58   178.9  739.45   188.8  738.48   208.7     739   278.3  739.04
   337.9  738.26   399.7  736.57   407.5  736.48   414.7  736.62   427.3  738.54
   437.3   744.9   447.2  754.39   457.2   762.5     487   781.1   496.9     786
   506.9  787.18   516.8  792.59   526.7  796.77   566.5  810.44   576.4  812.25
   586.4   812.4     646  816.35   655.9  816.33   675.8  814.74   705.6  807.83
#Mann= 3 , 0 , 0
       0      .1       0   399.7    .045       0   414.7      .1       0
Bank Sta=399.7,414.7
XS Rating Curve= 0 ,0
Exp/Cntr=0.3,0.1

Type RM Length L Ch R = 1 ,1695.8  ,110.6,111.6,112.7
XS GIS Cut Line= 2
     2138941.806      314110.702     2138821.258      313545.347
#Sta/Elev= 30
     9.8  755.88      49  750.16    58.8  749.87   107.8  740.43   117.6  739.31
   137.2   738.1   156.8  737.58   225.3   733.7   244.9  733.51   323.3  734.22
   333.1  733.81   343.2   732.6   352.7  731.85   358.2  733.01   362.5  733.92
   372.3  742.61   382.1  752.71   391.9  759.55   401.7  763.98   411.5  764.81
   421.3  767.21   431.1  770.13   440.9  772.46   450.7   774.3   489.9  780.67
   509.5  782.68   538.9  788.84   548.7  790.18   558.5  790.69   578.1   790.5
#Mann= 3 , 0 , 0
       0      .1       0   343.2    .045       0   358.2      .1       0
Bank Sta=343.2,358.2
XS Rating Curve= 0 ,0
Exp/Cntr=0.3,0.1

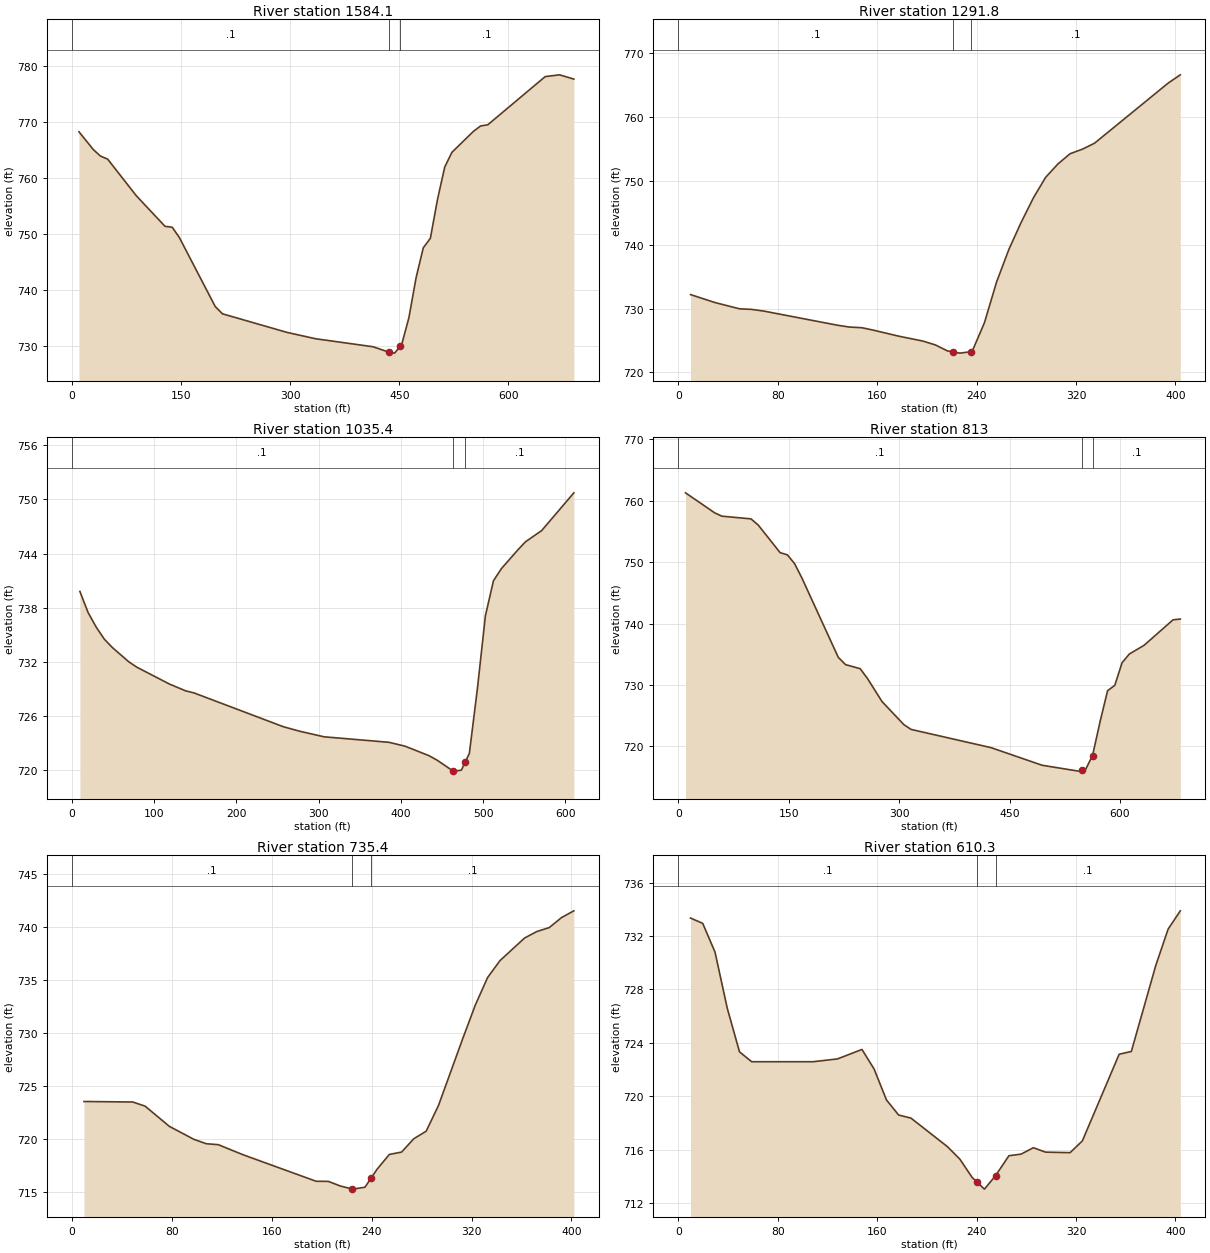
Type RM Length L Ch R = 1 ,1584.1  ,293,292.3,291.6
XS GIS Cut Line= 2
     2139049.675      314180.307     2138937.198      313499.703
#Sta/Elev= 30
     9.9  768.22    29.6  765.04    39.4  763.88    49.3  763.33    88.7  756.78
   128.1  751.32     138  751.16   147.8  749.32   197.1  736.98     207  735.68
   295.6  732.36   335.1  731.22   413.9  729.79   436.3   728.8   443.5  728.65
   451.3  729.87   453.3  730.19   463.2  734.99     473  742.09   482.9  747.46
   492.7  749.19   502.6   756.2   512.4  761.91   522.3  764.55   551.9   768.3
   561.7  769.26   571.6  769.47   650.4  778.08   670.1   778.4   689.8  777.64
#Mann= 3 , 0 , 0
       0      .1       0   436.3    .045       0   451.3      .1       0
Bank Sta=436.3,451.3
XS Rating Curve= 0 ,0
Exp/Cntr=0.3,0.1

Type RM Length L Ch R = 1 ,1291.8  ,258.2,256.4,254.6
XS GIS Cut Line= 2
      2139314.79      313915.697      2139213.56      313524.679
#Sta/Elev= 29
     9.9  732.18    29.6  730.93    49.3  729.95    59.1  729.86      69  729.59
   128.1  727.38   137.9  727.09   147.8  726.99   157.6  726.58   177.3  725.67
     197  724.89   206.9  724.29   216.7  723.35   220.7  723.21   226.6  723.01
   235.7  723.24   236.4  723.26   246.3  727.76   256.1  734.15     266  739.26
   275.8  743.46   285.7  747.32   295.5  750.53   305.4  752.63   315.2  754.24
   325.1  754.95   334.9  755.89   394.1   765.3   403.9   766.6
#Mann= 3 , 0 , 0
       0      .1       0   220.7    .045       0   235.7      .1       0
Bank Sta=220.7,235.7
XS Rating Curve= 0 ,0
Exp/Cntr=0.3,0.1

Type RM Length L Ch R = 1 ,1035.4  ,217.4,222.4,227.4
XS GIS Cut Line= 3
     2139291.811      313971.189     2139522.929      313687.339
     2139443.618      313456.364
#Sta/Elev= 30
     9.9  739.79    19.8  737.46    29.7  735.83    39.6  734.49    49.5  733.55
    69.3  731.98    79.1  731.38   118.7  729.51   138.5  728.75   148.4  728.53
   257.2  724.77     277  724.27   306.7  723.65   385.6  723.04   405.1  722.61
   434.4  721.55   444.2  721.05     463  719.88   463.7  719.84   473.5  719.94
     478   720.8   483.3  721.81     493  728.94   502.8  737.09   512.6  740.98
   522.3  742.33   541.9  744.37   551.6  745.31   571.2  746.55   610.3  750.74
#Mann= 3 , 0 , 0
       0      .1       0     463    .045       0     478      .1       0
Bank Sta=463,478
XS Rating Curve= 0 ,0
Exp/Cntr=0.3,0.1

Type RM Length L Ch R = 1 ,813     ,74.5,77.6,80.6
XS GIS Cut Line= 2
     2139762.633      314074.594      2139685.63      313396.961
#Sta/Elev= 30
     9.9  761.29    49.4  758.04    59.3  757.49    98.8  757.05   108.7  756.04
   138.4  751.55   148.3  751.19   158.1  749.75     168  747.42   217.4  734.51
   227.3  733.32   247.1  732.66     257  731.08   276.8  727.31   306.4  723.56
   316.3  722.77     425   719.8   494.2  716.94   543.6  715.98   547.8  716.11
   553.5  716.29   562.8  718.52   573.3  724.18   583.2  729.07     593  729.95
   602.9  733.63   612.8  735.05   632.6  736.45   672.1  740.61     682  740.74
#Mann= 3 , 0 , 0
       0      .1       0   547.8    .045       0   562.8      .1       0
Bank Sta=547.8,562.8
XS Rating Curve= 0 ,0
Exp/Cntr=0.3,0.1

Type RM Length L Ch R = 1 ,735.4   ,124.4,125.2,125.9
XS GIS Cut Line= 3
     2139762.907      313772.034      2139776.54      313498.568
      2139743.36      313374.864
#Sta/Elev= 30
     9.8  723.57    48.9  723.52    58.7  723.13    78.2  721.22    97.8     720
   107.6  719.59   117.3   719.5   136.9  718.56   195.6  716.05   205.4  716.04
   215.1   715.6   224.5  715.32   224.9  715.31   234.7  715.49   239.5  716.33
   244.5   717.2   254.2  718.58     264   718.8   273.8  720.06   283.7  720.77
   293.5  723.18   313.2  729.57   323.1  732.68   332.9  735.26   342.8  736.85
   362.5  738.98   372.3  739.59   382.2  739.96     392   740.9   401.9  741.54
#Mann= 3 , 0 , 0
       0      .1       0   224.5    .045       0   239.5      .1       0
Bank Sta=224.5,239.5
XS Rating Curve= 0 ,0
Exp/Cntr=0.3,0.1

Type RM Length L Ch R = 1 ,610.3   ,273.2,237.8,202.4
XS GIS Cut Line= 2
     2139873.953      313840.677     2139894.064      313437.268
#Sta/Elev= 30
     9.9  733.35    19.7  732.95    29.6   730.8    39.4  726.61    49.3  723.33
    59.1  722.59   108.4  722.59   128.1   722.8   147.8  723.51   157.6  722.04
   167.5  719.73   177.3   718.6   187.2  718.37   216.7  716.22   226.6  715.29
   236.4  713.93   240.3  713.58   246.3  713.05   255.3  714.06     266  715.55
   275.8  715.67   285.7  716.15   295.5  715.82   315.2  715.78   325.1  716.66
   354.7  723.15   364.5  723.36   384.2  729.81   394.1  732.52   403.9  733.89
#Mann= 3 , 0 , 0
       0      .1       0   240.3    .045       0   255.3      .1       0
Bank Sta=240.3,255.3
XS Rating Curve= 0 ,0
Exp/Cntr=0.3,0.1

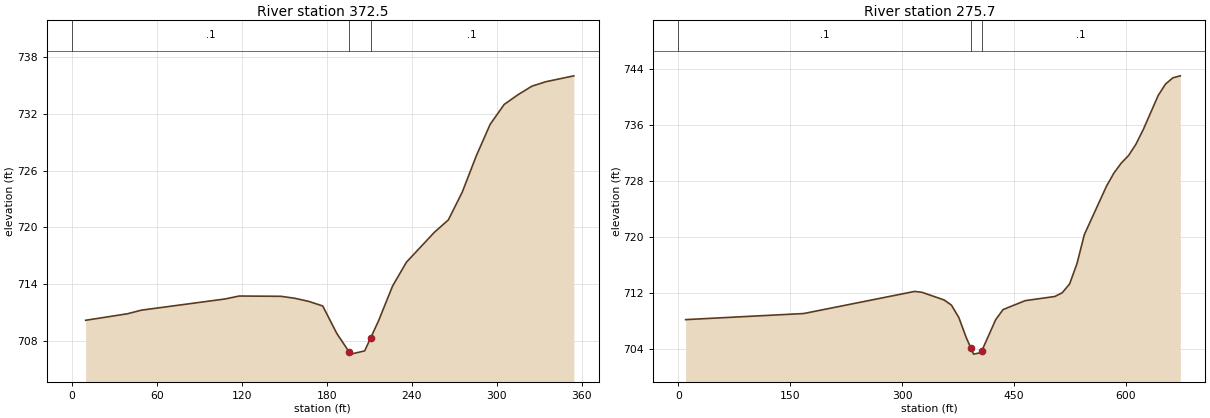
Type RM Length L Ch R = 1 ,372.5   ,97.9,96.7,95.6
XS GIS Cut Line= 2
     2140220.311      313446.045     2139866.686      313421.302
#Sta/Elev= 27
     9.8   710.2    39.4  710.89    49.2  711.27   108.3  712.45   118.2  712.76
   147.7  712.73   157.6  712.52   167.4  712.19   177.2  711.71   187.1  708.82
     196  706.83   196.9  706.63   206.8  706.97     211  708.33   216.6  710.14
   226.5  713.81   236.3  716.33     256  719.48   265.9  720.79   275.7  723.72
   285.6  727.54   295.4  730.87   305.3  732.97   315.1     734   324.9   734.9
   334.8  735.37   354.5  735.99
#Mann= 3 , 0 , 0
       0      .1       0     196    .045       0     211      .1       0
Bank Sta=196,211
XS Rating Curve= 0 ,0
Exp/Cntr=0.3,0.1

Type RM Length L Ch R = 1 ,275.7   ,269,275.7,282.4
XS GIS Cut Line= 2
     2140430.995      313392.984     2139763.653      313306.654
#Sta/Elev= 30
     9.9  708.19   168.2  709.06   316.7  712.21   326.6  712.09   356.2     711
   366.1  710.27     376  708.51   385.9  705.66   391.9  704.21   395.8  703.27
   405.7  703.48   406.9  703.75   425.5  708.19   435.4  709.63   465.1   710.9
   504.7  711.49   514.6  712.02   524.5  713.27   534.4  716.17   544.3  720.32
   573.9  727.21   583.8  729.07   593.7  730.51   603.6   731.6   613.5  733.22
   623.4  735.33   643.2  740.15   653.1  741.79     663  742.68   672.9  742.96
#Mann= 3 , 0 , 0
       0      .1       0   391.9    .045       0   406.9      .1       0
Bank Sta=391.9,406.9
XS Rating Curve= 0 ,0
Exp/Cntr=0.3,0.1

Chan Stop Cuts=-1
Use User Specified Reach Order=0